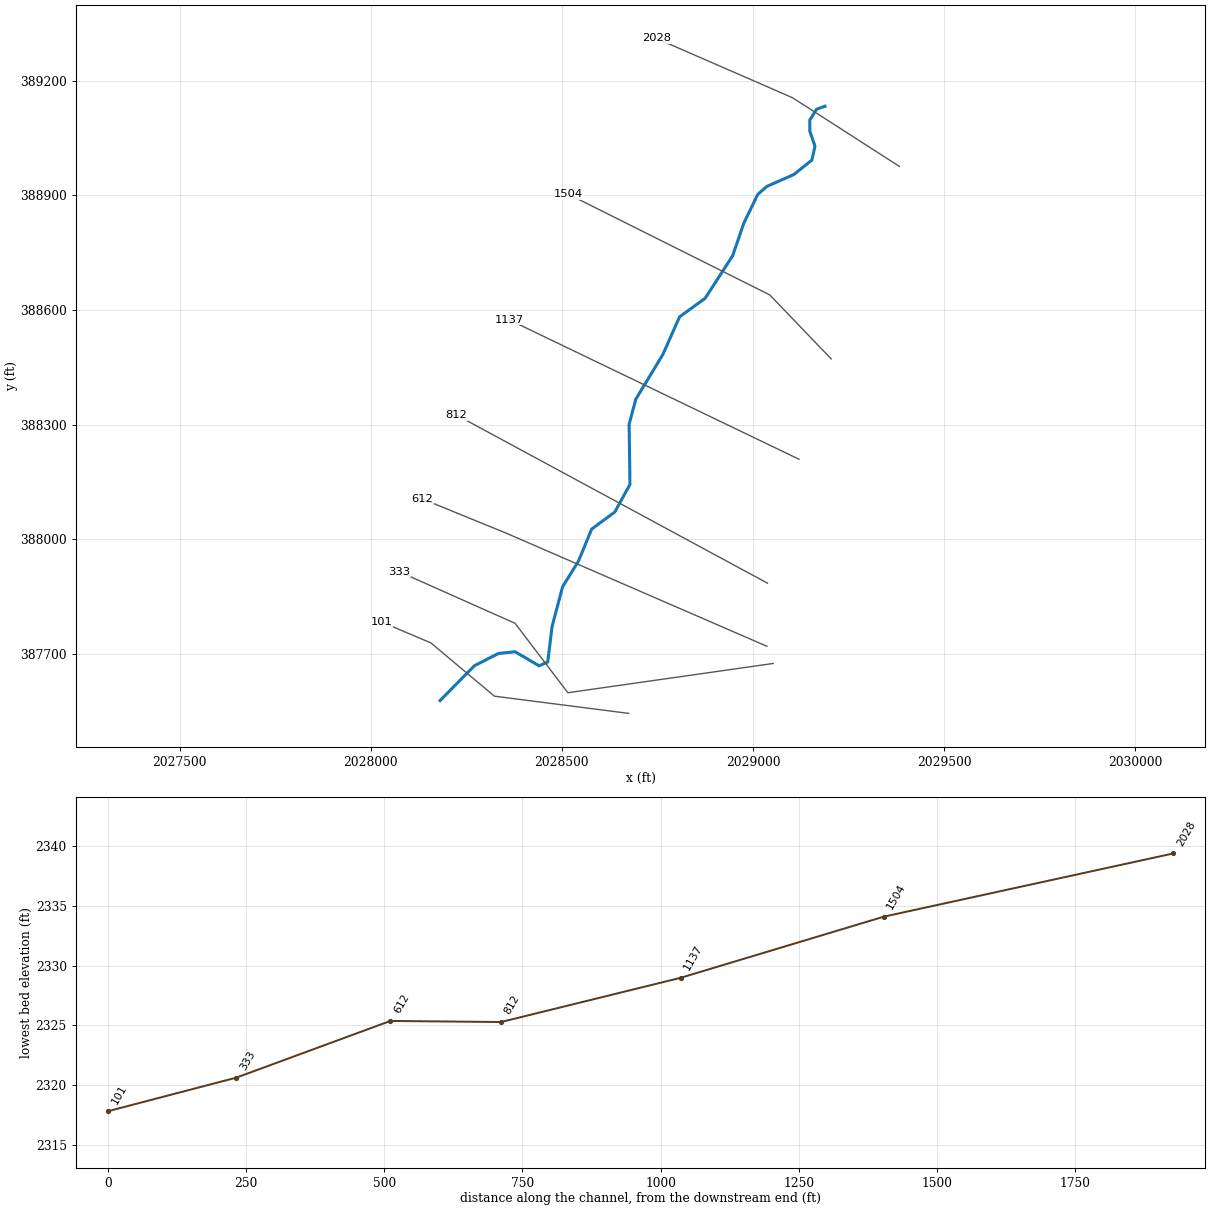
--- PINEYCK.prj (project) ---

Proj Title=PINEYCK
Current Plan=p02
Default Exp/Contr=0.3,0.1
English Units
Geom File=g01
Flow File=f01
Plan File=p02
Y Axis Title=Elevation
X Axis Title(PF)=Main Channel Distance
X Axis Title(XS)=Station
BEGIN DESCRIPTION:
Stream Name- Piney Creek
Flood Zone: Zone A
Greenbrier County, WV
County-Wide Study
WVDHSEM-2018-3, Flood Risk Project
HEC-RAS Version: 5.0.7
General Notes:
For the Hydrology Regression was used.
END DESCRIPTION:
DSS Export Rating Curves= 0
DSS Export Rating Curve Sorted= 0
DSS Export Volume Flow Curves= 0
DXF OffsetX= 0
DXF OffsetY= 0
DXF ScaleX= 1
DXF ScaleY= 10

--- PINEYCK.p02 (plan) ---

Plan Title=Floodplain
Program Version=5.07
Short Identifier=Floodplain
Geom File=g01
Flow File=f01
Subcritical Flow
K Sum by GR= 0
Std Step Tol= 0.01
Critical Tol= 0.01
Num of Std Step Trials= 20
Max Error Tol= 0.3
Flow Tol Ratio= 0.001
Split Flow NTrial= 30
Split Flow Tol= 0.02
Split Flow Ratio= 0.02
Log Output Level= 0
Friction Slope Method= 1
Unsteady Friction Slope Method= 2
Unsteady Bridges Friction Slope Method= 1
Parabolic Critical Depth
Global Vel Dist= 0 , 0 , 0
Global Log Level= 0
CheckData=False
Encroach Param=-1 ,0,0, 0
Computation Interval=1MIN
Output Interval=1HOUR
Instantaneous Interval=1HOUR
Mapping Interval=1HOUR
Computation Time Step Use Courant=        0
Computation Time Step Use Time Series=    0
Computation Time Step Count To Double=0
Computation Time Step Max Doubling=0
Computation Time Step Max Halving=0
Computation Time Step Residence Courant=0
Run HTab= 0
Run UNet= 0
Run Sediment= 0
Run PostProcess= 0
Run WQNet= 0
Run RASMapper= 0
UNET Theta= 1
UNET Theta Warmup= 1
UNET ZTol= 0.02
UNET ZSATol= 0.02
UNET MxIter= 20
UNET Max Iter WO Improvement= 0
UNET MaxInSteps= 0
UNET DtIC= 0
UNET DtMin= 0
UNET MaxCRTS= 20
UNET WFStab= 2
UNET SFStab= 1
UNET WFX= 1
UNET SFX= 1
UNET 1D Methodology=Finite Difference
UNET DSS MLevel= 4
UNET Pardiso=0
UNET DZMax Abort= 100
UNET Use Existing IB Tables=-1
UNET Froude Reduction=False
UNET Froude Limit= 0.8
UNET Froude Power= 4
UNET D1 Cores= 0
UNET D2 Coriolis=0
UNET D2 Cores= 0
UNET D2 Theta= 1
UNET D2 Theta Warmup= 1
UNET D2 Z Tol= 0.01
UNET D2 Volume Tol= 0.01
UNET D2 Max Iterations= 20
UNET D2 Equation= 0
UNET D2 RampUpFraction=0.1
UNET D2 TimeSlices= 1
UNET D2 BCVolumeCheck=0
UNET D1D2 MaxIter= 0
UNET D1D2 ZTol=0.01
UNET D1D2 QTol=0.1
UNET D1D2 MinQTol=1
Write IC File= 0
Write IC File at Fixed DateTime=0
Write IC File at Sim End=0
Echo Input=False
Echo Parameters=False
Echo Output=False
Write Detailed= 0
HDF Write Warmup=0
HDF Write Time Slices=0
HDF Flush=0
HDF Face Node Velocities=0
HDF Compression= 1
HDF Chunk Size= 1
HDF Spatial Parts= 1
HDF Use Max Rows=0
HDF Fixed Rows= 1
Calibration Method= 0
Calibration Iterations= 20
Calibration Max Change=0.05
Calibration Tolerance=0.2
Calibration Maximum=1.5
Calibration Minimum=0.5
Calibration Optimization Method= 1
WQ AD Non Conservative
WQ ULTIMATE=-1
WQ Max Comp Step=1HOUR
WQ Output Interval=15MIN
WQ Output Selected Increments= 0
WQ Output face flow=0
WQ Output face velocity=0
WQ Output face area=0
WQ Output face dispersion=0
WQ Output cell volume=0
WQ Output cell surface area=0
WQ Output cell continuity=0
WQ Output cumulative cell continuity=0
WQ Output face conc=0
WQ Output face dconc_dx=0
WQ Output face courant=0
WQ Output face peclet=0
WQ Output face adv mass=0
WQ Output face disp mass=0
WQ Output cell mass=0
WQ Output cell source sink temp=0
WQ Output nsm pathways=0
WQ Output nsm derived pathways=0
WQ Output MaxMinRange=-1
WQ Daily Max Min Mean=-1
WQ Daily Range=0
WQ Daily Time=0
WQ Create Restart=0
WQ Fixed Restart=0
WQ System Summary=0
WQ Write To DSS=0
WQ Use Fixed Temperature=0
Sorting and Armoring Iterations= 10
XS Update Threshold= 0.02
Bed Roughness Predictor= 0
Hydraulics Update Threshold= 0.02
Energy Slope Method= 1
Volume Change Method= 1
Sediment Retention Method= 0
XS Weighting Method= 0
Number of US Weighted Cross Sections= 1
Number of DS Weighted Cross Sections= 1
Upstream XS Weight=0
Main XS Weight=1
Downstream XS Weight=0
Number of DS XS's Weighted with US Boundary= 1
Upstream Boundary Weight= 1
Weight of XSs Associated with US Boundary= 0
Number of US XS's Weighted with DS Boundary= 1
Downstream Boundary Weight= 0.5
Weight of XSs Associated with DS Boundary= 0.5
Percentile Method= 0
Sediment Output Level= 3
Mass or Volume Output= 0
Output Increment Type= 1
Profile and TS Output Increment= 1
XS Output Flag= 0
XS Output Increment= 10
Write Gradation File= 0
Read Gradation Hotstart= 0
Write HDF5 File= 1
Write Binary Output= 1
Write DSS Sediment File= 0
SV Curve= 0
Specific Gage Flag= 0

--- PINEYCK.f01 (steady flow) ---

Flow Title=Flow 01
Program Version=5.07
Number of Profiles= 6
Profile Names=f1p,f10p,f4p,f2p,f02p,f1pplus
River Rch & RM=PINEYCK,Main            ,2028
     478     251     335     404     671     708
River Rch & RM=PINEYCK,Main            ,333
     845     453     599     718    1170    1250
Boundary for River Rch & Prof#=PINEYCK,Main            , 1
Up Type= 0
Dn Type= 3
Dn Slope=0.01254
DSS Import GetInterval= 0
DSS Import GetPeak= 0
DSS Import FillOption= 0

--- PINEYCK.g01 (geometry) ---

Geom Title=USGS LIDAR
Program Version=5.07

River Reach=PINEYCK         ,Main
Reach XY= 28
2029188.45281066389133.1271086042029166.50172143389125.383319989
2029148.67146696 389097.010197522029148.56692572389068.212123334
2029162.20614402389028.1404419542029154.00694211388992.104655549
2029106.49984242 388954.194965052029036.69295792388923.553325206
2029012.51742508 388902.458982082028976.09162201388827.381250978
2028946.73658605388741.8551424592028874.88425617388630.660671979
2028807.87614401388581.9471086112028763.86016105388482.940526009
2028693.42244609388366.5933652372028675.98197876388301.133651033
2028678.20112972388143.6836311372028638.46326442388071.439715147
2028577.98445703388026.8413467262028543.25912686387942.556498826
2028502.10592668387876.3803068252028474.42930393387772.239430517
2028463.11518766 387679.278476672028440.53224771387669.144937992
2028377.81625281387705.9364598542028334.22066043 387701.50828065
2028271.37800799387669.4803122132028181.39217691387578.211961895

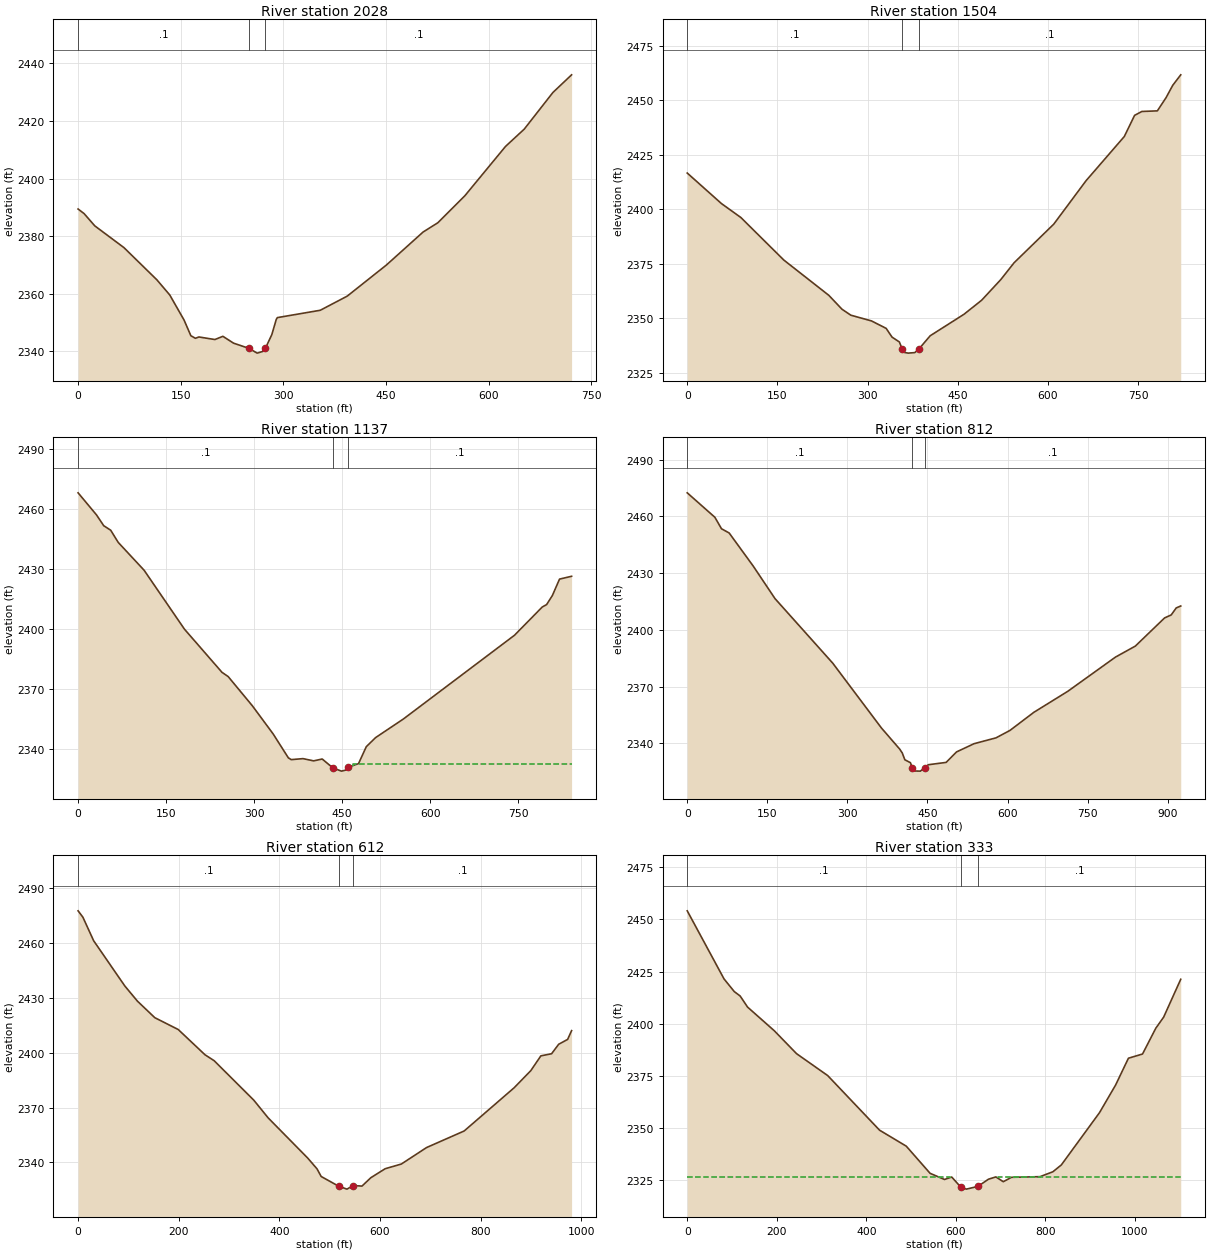
Type RM Length L Ch R = 1 ,2028    ,519.7,524.1,522.5
XS GIS Cut Line= 3
2029382.85784192388975.7281868982029103.30053012389155.347136029
2028746.76366868389310.656753699
#Sta/Elev= 30
       0 2389.42     8.8 2387.82    24.4 2383.57      67 2376.02   115.2 2364.82
     134 2359.56   154.9 2350.85   164.8 2345.42   171.5 2344.53   176.5 2344.99
   199.9  2344.1   211.6 2345.22   227.2 2342.84   249.8 2341.03   261.7 2339.38
   270.1 2339.99   273.6    2341   283.1  2345.8   289.6 2351.07   291.2 2351.71
   353.9 2354.26   393.3 2359.17   450.5 2369.96   504.2 2381.43   525.7 2384.64
   565.1 2393.99   624.6 2411.14     652 2417.16   693.9 2429.88721.1833 2436.01
#Mann= 3 , 0 , 0
       0      .1       0   249.8     .04       0   273.6      .1       0
Bank Sta=249.8,273.6
XS Rating Curve= 0 ,0
Exp/Cntr(USF)=0,0
Exp/Cntr=0.3,0.1

Type RM Length L Ch R = 1 ,1504    ,365.9,367.3,366.6
XS GIS Cut Line= 3
2029204.58941121388471.9848182822029043.87771988388639.449101682
2028517.17553821388902.800192514
#Sta/Elev= 30
       0  2416.6    56.9 2402.62    89.2 2396.23   160.7 2376.73   235.5 2360.58
   257.5 2354.19   272.2 2351.47   306.5 2348.85   330.9 2345.44   340.7 2341.43
   352.9 2339.21   357.8 2335.83   360.2 2334.47   367.5 2334.09   378.6 2334.33
   385.9 2336.14   404.2 2342.05   460.5 2351.91   489.9 2358.36   521.7 2367.81
   543.7 2375.48   609.7 2393.18   663.5  2413.1   727.1 2433.34   744.2 2443.03
   756.3 2444.81   782.1 2445.09   796.7 2451.21   807.7 2456.81820.9755  2461.6
#Mann= 3 , 0 , 0
       0      .1       0   357.8     .04       0   385.9      .1       0
Bank Sta=357.8,385.9
XS Rating Curve= 0 ,0
Exp/Cntr(USF)=0,0
Exp/Cntr=0.3,0.1

Type RM Length L Ch R = 1 ,1137    ,326.1,325.2,326.3
XS GIS Cut Line= 2
 2029120.4070967 388209.534073062028362.61620855 388574.17404498
#Sta/Elev= 30
       0 2468.14    31.4 2457.09    43.7  2451.7    55.6 2449.43    68.4 2443.35
   112.5 2429.43   181.3 2399.95   245.2 2378.39   255.8 2376.24   296.9 2361.68
   332.3 2347.62   358.3 2335.63   363.2 2334.73   383.2 2335.23   401.4 2334.11
     416 2335.04   434.2 2330.58   448.8 2328.98   456.1  2329.5   459.7 2330.85
   477.9 2332.73   491.1  2341.2     507 2345.75   554.4 2355.06   743.7 2396.93
   790.9 2411.03   798.4 2412.26   808.2 2416.78   820.4    2425840.9574 2426.41
#Mann= 3 , 0 , 0
       0      .1       0   434.2     .04       0   459.7      .1       0
#XS Ineff= 2 , 0
                          468.68         2332.64
Permanent Ineff=
       F       F
Bank Sta=434.2,459.7
XS Rating Curve= 0 ,0
Exp/Cntr(USF)=0,0
Exp/Cntr=0.3,0.1

Type RM Length L Ch R = 1 ,812     ,195.8,200.2,200.2
XS GIS Cut Line= 2
2029037.87541581387885.4096535752028224.56321507388325.078426302
#Sta/Elev= 30
       0 2472.51    51.8 2459.57    64.2  2453.5    78.5 2451.28   123.5 2433.81
   164.5 2416.52   272.6  2382.4   364.1    2348     398 2336.95   402.9 2334.85
   407.7 2331.28   418.1 2329.76   421.8 2326.91   425.6 2325.36   436.7 2325.28
   444.9 2327.09   451.7 2328.67     485 2329.89   504.5 2335.44   537.4  2339.8
   578.5 2342.89   604.6 2346.81   649.3 2356.38   712.7 2367.46   802.2 2385.59
   839.5 2391.43   894.3 2406.33   906.7 2407.91   916.1 2411.62 924.546 2412.64
#Mann= 3 , 0 , 0
       0      .1       0   421.8     .04       0   444.9      .1       0
Bank Sta=421.8,444.9
XS Rating Curve= 0 ,0
Exp/Cntr(USF)=0,0
Exp/Cntr=0.3,0.1

Type RM Length L Ch R = 1 ,612     ,290.4,278.7,272.1
XS GIS Cut Line= 3
 2029036.3748398  387720.34629182028355.11332847388015.959766979
 2028134.5286541388105.994327947
#Sta/Elev= 30
       0 2477.56     9.5 2474.11    30.9 2461.22    92.9 2436.46   117.9 2428.19
   152.5 2419.12     199 2412.66   252.3 2398.83   270.5 2395.59   349.2 2374.03
   377.8 2364.33   456.5 2342.33   474.9 2336.46   483.1  2332.3   518.3 2326.91
   534.4 2325.37   546.9 2327.32   564.3 2327.03   581.8  2331.6   610.3 2336.52
   642.5 2339.09   692.6  2348.1   767.4 2357.17   866.7  2380.8   899.9 2390.19
   919.8 2398.25   941.1  2399.4   955.2 2404.58     973 2407.24980.8851 2412.04
#Mann= 3 , 0 , 0
       0      .1       0   518.3     .04       0   546.9      .1       0
Bank Sta=518.3,546.9
XS Rating Curve= 0 ,0
Exp/Cntr(USF)=0,0
Exp/Cntr=0.3,0.1

Type RM Length L Ch R = 1 ,333     ,242.9,232.4,236.3
XS GIS Cut Line= 4
2029052.88117597387675.329011316 2028515.6749622387598.799634493
2028377.62196871387780.3693324462028074.50561346387915.421173898
#Sta/Elev= 30
       0 2454.14    82.2 2421.48     105 2415.41   118.2 2413.28   134.8 2407.96
   194.5 2396.61   244.2 2385.62   313.8 2375.11   429.7 2348.91   489.4 2341.23
   542.6 2328.21   574.8 2325.26   590.9 2326.43   611.3 2321.58   623.6 2320.63
   649.4 2321.94   673.1  2325.4   689.6 2326.49   706.1 2324.19   724.3 2326.29
   788.2 2326.61   816.9 2328.95   835.8 2332.24   921.1 2357.32     957 2370.55
   985.7 2383.43  1017.2 2385.45  1046.8  2397.8  1064.4 2403.151102.564  2421.3
#Mann= 3 , 0 , 0
       0      .1       0   611.3     .04       0   649.4      .1       0
#XS Ineff= 2 , 0
          586.64 2326.58  693.54         2326.34
Permanent Ineff=
       F       F
Bank Sta=611.3,649.4
XS Rating Curve= 0 ,0
Exp/Cntr(USF)=0,0
Exp/Cntr=0.3,0.1

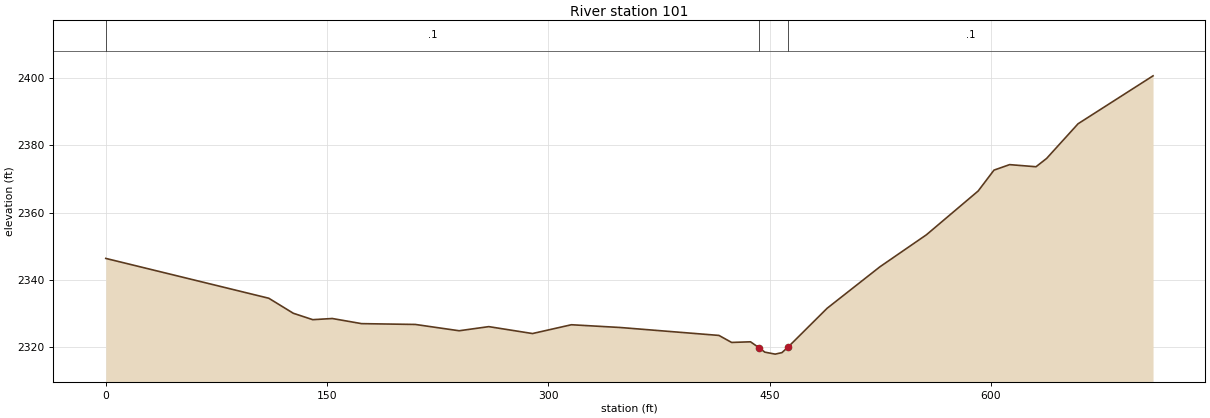
Type RM Length L Ch R = 1 ,101     ,82,82,82
XS GIS Cut Line= 4
2028674.73601991387544.7788979132028323.60123213387589.796178397
2028157.03729434387729.3497478972028029.48833297387783.370484478
#Sta/Elev= 30
       0 2346.33   110.5 2334.46   127.1 2329.99   140.3 2328.08   153.5 2328.43
   173.4  2326.9   209.8 2326.66   239.5 2324.78   259.6 2326.01   289.2 2323.95
   315.6 2326.57   348.7 2325.75   415.6 2323.39   424.2  2321.3     437 2321.49
   442.9 2319.68   446.7 2318.41   453.7 2317.82   458.3 2318.27   462.7 2320.03
   488.9 2331.47   524.7 2343.83   556.2 2353.36   591.3 2366.41     602 2372.62
   612.6 2374.26   630.5 2373.63   637.7 2376.11     659 2386.43709.8246 2400.71
#Mann= 3 , 0 , 0
       0      .1       0   442.9     .04       0   462.7      .1       0
Bank Sta=442.9,462.7
XS Rating Curve= 0 ,0
Exp/Cntr(USF)=0,0
Exp/Cntr=0.3,0.1
LCMann Table=0

Chan Stop Cuts=-1
Use User Specified Reach Order=0
Composite Channel Slope=5